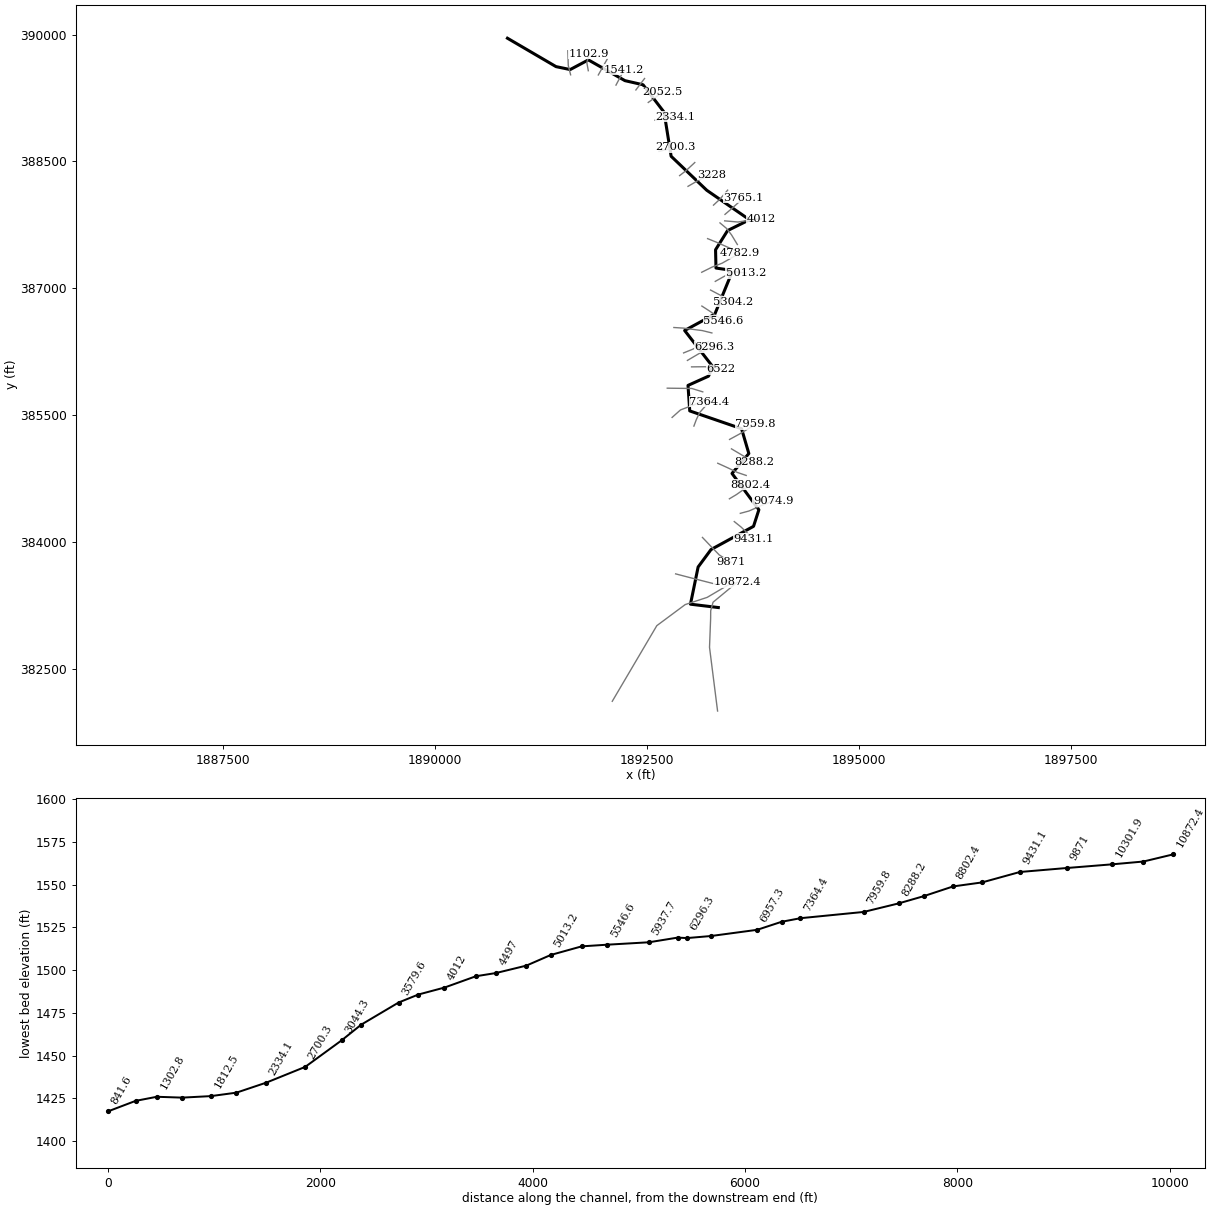
--- BULLRN1.prj (project) ---

Proj Title=BULLRN1
Current Plan=p01
Default Exp/Contr=0,0
English Units
Geom File=g01
Flow File=f01
Plan File=p01
BEGIN DESCRIPTION:
END DESCRIPTION:
DSS Export Rating Curves= 0
DSS Export Rating Curve Sorted= 0
DSS Export Volume Flow Curves= 0
DXF OffsetX= 0
DXF OffsetY= 0
DXF ScaleX= 0
DXF ScaleY= 0

--- BULLRN1.p01 (plan) ---

Plan Title=Floodplain
Program Version=4.00
Geom File=g01
Flow File=f01
K Sum by GR=0
Std Step Tol=0.01
Critical Tol=0.01
Num of Std Step Trials=20
Max Error Tol=0.3
Flow Tol Ratio=0.001
Split Flow NTrial=30
Split Flow Tol=0.02
Split Flow Ratio=0.02
Log Output Level=0
Friction Slope Method=1
Unsteady Friction Slope Method=2
Unsteady Bridges Friction Slope Method=1
Global Log Level=0
CheckData=False
Run HTab=0
Run UNet=0
Run PostProcess=0
UNET Theta=0
UNET Theta Warmup=0
UNET ZTol=0
UNET ZSATol=0
UNET MxIter=0
UNET MaxInSteps=0
UNET DtIC=0
UNET DtMin=0
UNET MaxCRTS=0
UNET WFStab=0
UNET SFStab=0
UNET WFX=0
UNET SFX=0
UNET DSS MLevel=0
UNET DZMax Abort=0
UNET Convert EG Bridges=0
UNET Use Existing IB Tables=0
UNET Froude Limit=0
UNET Froude Power=0
Write IC File=0
Echo Input=False
Echo Output=False
Write Detailed=0

--- BULLRN1.f01 (steady flow) ---

Flow Title=NFF Regression Equation
Program Version=4.10
Number of Profiles= 1
Profile Names=P100yr
River Rch & RM=BULLRN1,Main            ,10872.4
516.9828
River Rch & RM=BULLRN1,Main            ,10594.6
815.0151
River Rch & RM=BULLRN1,Main            ,5013.2
870.4085
River Rch & RM=BULLRN1,Main            ,4782.9
1067.063
River Rch & RM=BULLRN1,Main            ,241.6
1143.175
Boundary for River Rch & Prof#=BULLRN1,Main            , 1
Up Type= 0
Dn Type= 1
Dn Known WS=1419.16
DSS Import GetInterval= 0
DSS Import GetPeak= 0
DSS Import FillOption= 0

--- BULLRN1.g01 (geometry) ---

Geom Title=USGS 10m DEM
Program Version=4.10

River Reach=BULLRN1         ,Main
Reach XY= 30
     1893340.064      383228.554     1893011.896      383268.234
     1893101.957      383707.687     1893253.867       383913.85
     1893755.169      384188.373     1893818.128      384384.312
     1893501.262      384813.373      1893699.83      385048.833
      1893614.11      385341.802     1893003.216      385552.305
       1892982.8      385853.578     1893224.653      385963.049
     1893273.398      386076.394     1892943.199       386502.48
     1893298.726      386695.925     1893485.405      387152.545
     1893455.603      387219.654      1893312.46      387240.673
     1893307.589      387456.721     1893449.179      387683.382
     1893707.426       387811.42     1893203.953      388159.727
      1892783.87       388561.59     1892700.705      389082.669
     1892453.085      389406.472     1892239.327        389455.3
     1891808.554      389700.526     1891594.209      389586.321
     1891427.172      389620.978     1890854.778      389956.602

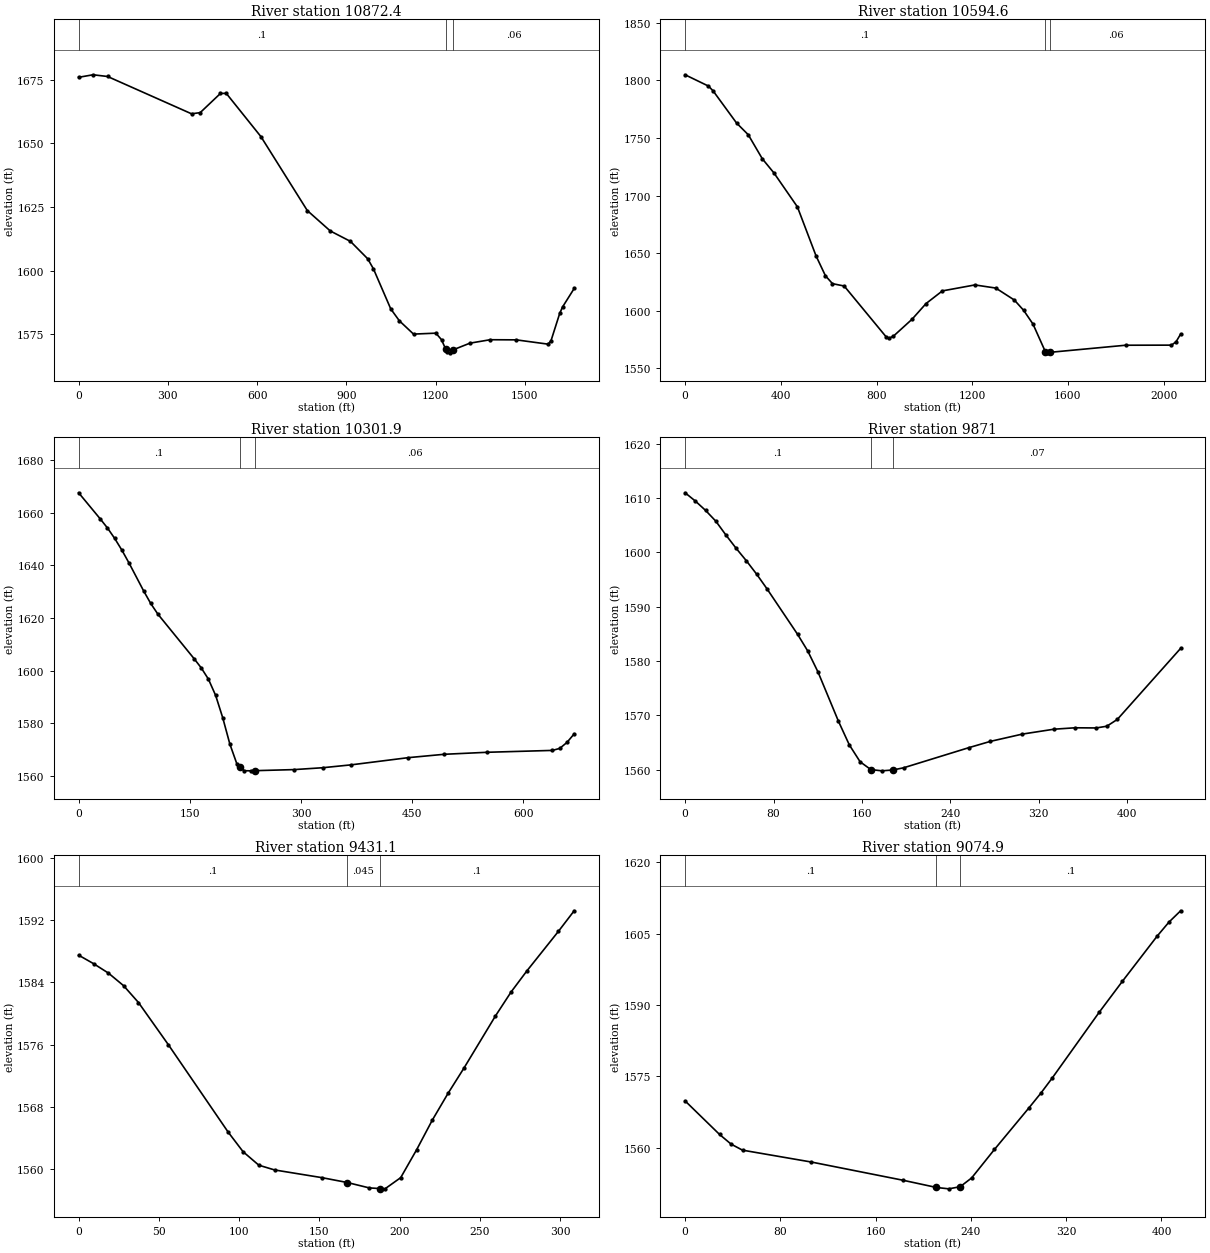
Type RM Length L Ch R = 1 ,10872.4 ,302.5,277.8,252
XS GIS Cut Line= 6
     1893331.328      382005.644      1893236.36      382758.579
     1893249.397      383096.999     1893250.273      383190.757
     1893278.051      383291.452     1893562.773      383527.563
#Sta/Elev= 30
       0 1675.92    48.6 1676.91    97.3 1676.24   379.4 1661.59   408.6 1662.04
   476.7 1669.58   496.2 1669.62     613 1652.58   768.6 1623.59     846 1615.56
   913.7 1611.48   971.8 1604.63   991.1 1600.65  1049.2 1584.95  1078.2 1580.27
  1125.7 1575.06  1200.8 1575.43  1219.8 1572.86  1233.4 1569.24  1238.8 1567.87
  1248.3  1567.7  1257.8 1568.84  1315.3  1571.5  1383.4 1572.85    1471  1572.8
  1578.1 1571.11  1587.8 1572.44    1617 1583.16  1626.7 1585.73  1665.7 1592.98
#Mann= 3 , 0 , 0
       0      .1       0  1233.4    .045       0  1257.8     .06       0
Bank Sta=1233.4,1257.8
XS Rating Curve= 0 ,0
Exp/Cntr=0.3,0.1

Type RM Length L Ch R = 1 ,10594.6 ,306.8,292.7,278.2
XS GIS Cut Line= 5
     1892090.008      382120.662     1892614.984       383014.28
     1892949.926      383263.674     1893208.606      383348.743
     1893505.481      383524.091
#Sta/Elev= 30
       0 1804.95    97.8 1795.12   117.3  1790.9   215.1 1763.07     264 1752.89
   322.7 1732.03   371.5 1719.69   469.3  1690.3   547.5 1647.63   586.6 1630.44
     616 1623.62   664.9 1621.56   840.9 1577.27   850.6 1576.12   870.2 1577.95
   948.4 1592.69  1007.1 1606.36  1075.3 1617.33  1211.2 1622.51  1298.6 1619.79
  1376.3 1609.36  1415.2 1600.39    1454 1588.54  1505.6  1564.6  1512.4 1563.56
  1525.6 1564.02  1841.2 1570.17  2032.8 1570.25    2052 1573.18  2071.1 1579.86
#Mann= 3 , 0 , 0
       0      .1       0  1505.6    .045       0  1525.6     .06       0
Bank Sta=1505.6,1525.6
XS Rating Curve= 0 ,0
Exp/Cntr=0.3,0.1

Type RM Length L Ch R = 1 ,10301.9 ,444.7,430.9,417.1
XS GIS Cut Line= 4
     1892837.078      383626.521     1893015.898      383579.646
     1893314.509      383503.257     1893484.648       383546.66
#Sta/Elev= 30
       0 1667.52    29.2 1657.59    38.9 1654.15    48.6 1650.21    58.4 1645.72
    68.1  1640.8    87.6 1630.32    97.3 1625.48     107 1621.41   155.7 1604.56
   165.4 1601.05   175.1 1596.77   184.9 1590.57   194.5 1582.04   204.1 1572.07
   213.8 1564.36   217.5 1563.44   223.4 1561.98     233 1561.93   237.5 1561.99
   290.8  1562.4   329.3 1563.11   367.9 1564.21   444.9 1566.94   493.1 1568.21
   551.6 1568.98   639.4 1569.69   649.2 1570.45   658.9  1572.7   668.7 1575.96
#Mann= 3 , 0 , 0
       0      .1       0   217.5    .045       0   237.5     .06       0
Bank Sta=217.5,237.5
XS Rating Curve= 0 ,0
Exp/Cntr=0.3,0.1

Type RM Length L Ch R = 1 ,9871    ,438.6,439.8,440.7
XS GIS Cut Line= 4
     1893153.051      384057.077     1893248.537      383956.382
     1893350.967      383850.479      1893488.12      383763.674
#Sta/Elev= 28
       0 1610.98     9.2 1609.47    18.5 1607.74    27.8 1605.75      37 1603.18
    46.3 1600.72    55.5 1598.44    64.8 1595.97      74 1593.32   101.8  1584.9
     111 1581.83   120.3 1577.95   138.8 1568.88   148.6 1564.54   158.4 1561.42
   168.1 1559.99   178.1 1559.76   188.1 1559.92   197.7 1560.32   256.6 1564.02
   276.3 1565.19   305.2 1566.53   333.8 1567.43   352.9 1567.69     372 1567.66
   381.6 1567.98   391.1 1569.23   448.4 1582.32
#Mann= 3 , 0 , 0
       0      .1       0   168.1    .045       0   188.1     .07       0
Bank Sta=168.1,188.1
XS Rating Curve= 0 ,0
Exp/Cntr=0.3,0.1

Type RM Length L Ch R = 1 ,9431.1  ,326.5,356.2,385.7
XS GIS Cut Line= 3
     1893528.051      384244.577     1893607.912      384180.341
     1893757.217      384037.979
#Sta/Elev= 25
       0 1587.49     9.3  1586.4    18.6 1585.18      28 1583.57    37.3  1581.4
    55.9 1575.98    93.2 1564.73   102.5 1562.21   112.3 1560.48   122.1 1559.87
   151.6 1558.88   167.5 1558.25   181.1 1557.56   187.5 1557.48   190.9 1557.44
   200.7 1558.88   210.6 1562.46   220.4 1566.28   230.2 1569.72     240 1572.93
   259.7 1579.66   269.5 1582.76   279.3 1585.46     299 1590.56   308.8  1593.2
#Mann= 3 , 0 , 0
       0      .1       0   167.5    .045       0   187.5      .1       0
Bank Sta=167.5,187.5
XS Rating Curve= 0 ,0
Exp/Cntr=0.3,0.1

Type RM Length L Ch R = 1 ,9074.9  ,267.5,272.5,277.5
XS GIS Cut Line= 4
     1893599.231      384341.799     1893701.662      384369.577
     1893850.967      384435.549      1893988.12      384487.632
#Sta/Elev= 19
       0 1569.82    28.9 1562.78    38.6 1560.74    48.2 1559.47   106.1 1556.97
   182.9 1553.15     211 1551.63   221.4 1551.34     231 1551.79   240.6 1553.63
   259.8 1559.63   288.9 1568.41   298.7 1571.44   308.5 1574.71   347.6 1588.41
   367.2 1594.96   396.5 1604.49   406.3  1607.4   416.1 1609.78
#Mann= 3 , 0 , 0
       0      .1       0     211    .045       0     231      .1       0
Bank Sta=211,231
XS Rating Curve= 0 ,0
Exp/Cntr=0.3,0.1

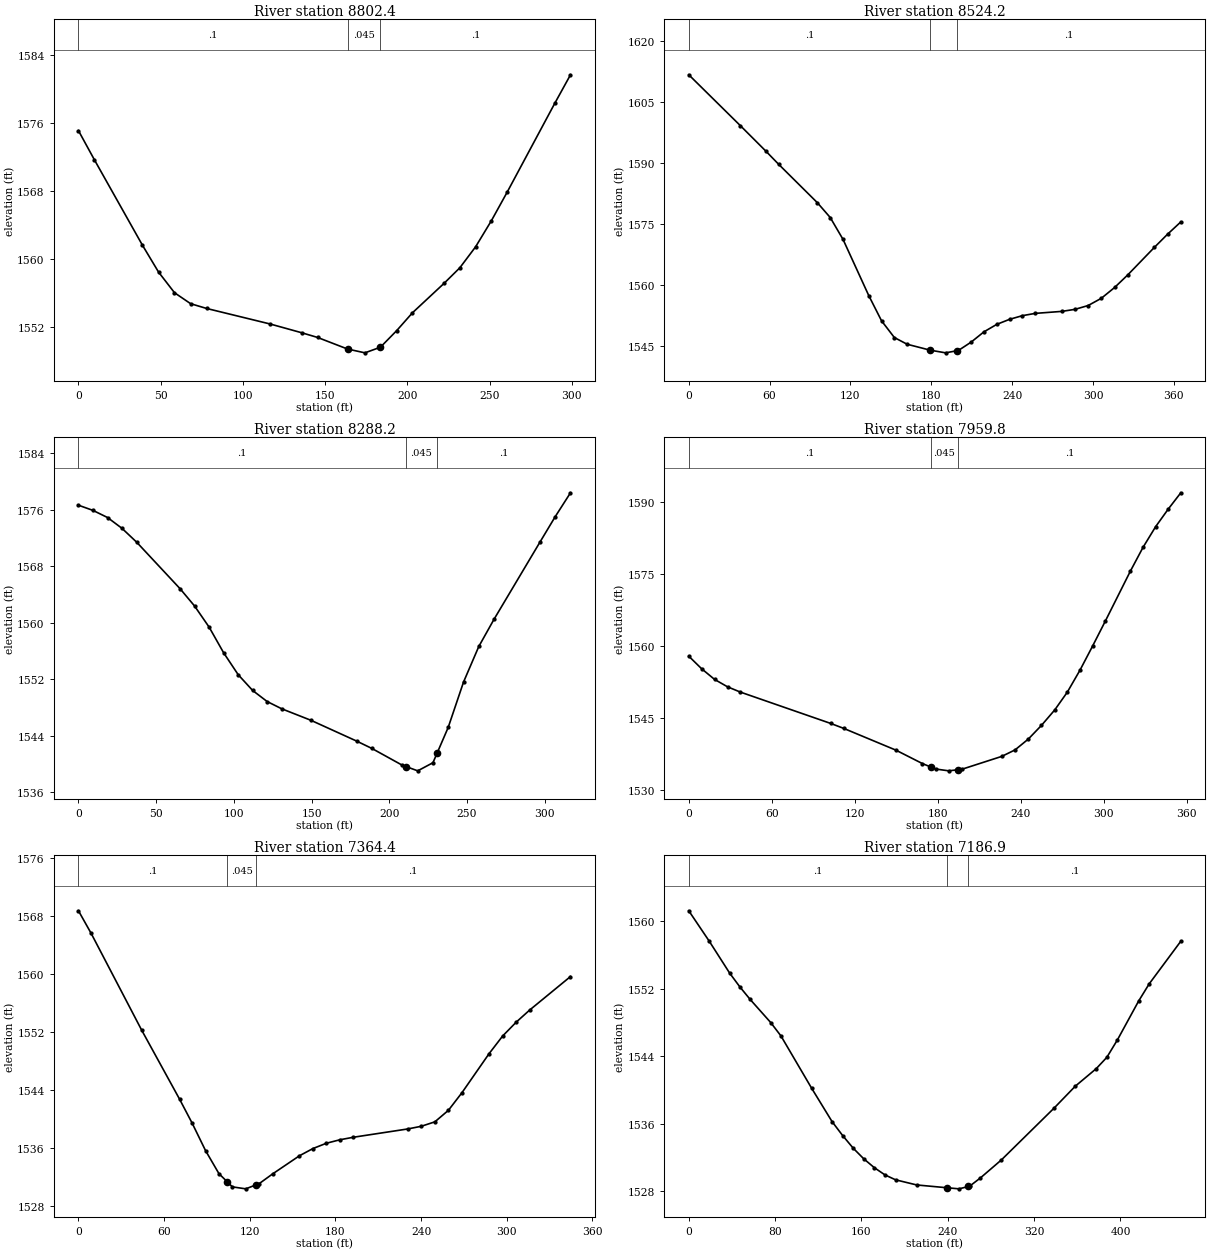
Type RM Length L Ch R = 1 ,8802.4  ,305,278.3,251.3
XS GIS Cut Line= 3
     1893470.759      384513.674     1893554.092      384564.021
     1893719.023      384680.341
#Sta/Elev= 22
       0 1575.13     9.7  1571.7    38.9 1561.66    48.7  1558.5    58.4 1556.07
    68.2 1554.78    77.9 1554.22   116.6 1552.39   135.8 1551.36   145.4 1550.81
   163.6 1549.45   174.2    1549   183.6 1549.66   193.5 1551.61   203.1 1553.71
   222.3 1557.17   231.9    1559   241.5 1561.47   251.1 1564.54   260.7  1567.9
   289.6 1578.33   299.2  1581.7
#Mann= 3 , 0 , 0
       0      .1       0   163.6    .045       0   183.6      .1       0
Bank Sta=163.6,183.6
XS Rating Curve= 0 ,0
Exp/Cntr=0.3,0.1

Type RM Length L Ch R = 1 ,8524.2  ,237.5,236,234.4
XS GIS Cut Line= 4
     1893333.606      384933.813     1893455.134      384878.257
     1893566.245      384824.438     1893668.676      384789.716
#Sta/Elev= 30
       0 1611.64    38.2 1599.16    57.3 1592.84    66.8  1589.6    95.4  1580.2
     105 1576.54   114.5 1571.16   133.6 1557.34   143.1 1551.13   152.6 1547.03
   162.1 1545.38   179.1 1543.93   190.6 1543.27   199.1 1543.79   200.1 1543.85
   209.6 1545.91   219.1 1548.44   228.6 1550.27   238.1 1551.51   247.6 1552.41
   257.1 1552.97   276.8 1553.46   286.6 1553.96   296.4  1554.9   306.2 1556.68
   316.1 1559.35   325.9 1562.46   345.6 1569.21   355.4 1572.45   365.2 1575.46
#Mann= 3 , 0 , 0
       0      .1       0   179.1    .045       0   199.1      .1       0
Bank Sta=179.1,199.1
XS Rating Curve= 0 ,0
Exp/Cntr=0.3,0.1

Type RM Length L Ch R = 1 ,8288.2  ,301.5,328.4,355.4
XS GIS Cut Line= 3
     1893495.064      385103.952     1893623.537      385027.563
      1893769.37      384945.966
#Sta/Elev= 28
       0 1576.64     9.3 1575.91    18.7  1574.9      28 1573.37    37.4 1571.42
    65.4 1564.82    74.7 1562.38    84.1 1559.38    93.4 1555.76   102.8 1552.65
   112.1 1550.42   121.4 1548.86   130.8 1547.83   149.5 1546.21     179 1543.26
   188.8 1542.22   208.4 1539.84   210.7 1539.66   218.3 1539.05   228.1  1540.2
   230.7 1541.52   237.9 1545.19   247.8 1551.63   257.6 1556.65   267.4  1560.5
   296.9  1571.4   306.8 1575.03   316.6  1578.4
#Mann= 3 , 0 , 0
       0      .1       0   210.7    .045       0   230.7      .1       0
Bank Sta=210.7,230.7
XS Rating Curve= 0 ,0
Exp/Cntr=0.3,0.1

Type RM Length L Ch R = 1 ,7959.8  ,580.3,595.4,609.5
XS GIS Cut Line= 4
     1893472.495      385215.063     1893587.078      385277.563
     1893701.662      385347.007     1893779.787      385393.882
#Sta/Elev= 28
       0 1557.95     9.3 1555.33    18.6 1553.12      28 1551.57    37.3 1550.47
   102.6 1543.94   111.9 1542.92   149.7 1538.38   168.8 1535.59   174.8 1534.88
   178.4 1534.45   187.9 1534.07   194.8 1534.31   197.5 1534.41   226.2 1537.08
   235.8 1538.43   245.4 1540.69   254.9 1543.54   264.5 1546.76   273.6 1550.47
   282.7 1555.02   291.8 1560.03     301 1565.23   319.2 1575.69   328.3 1580.62
   337.4 1584.92   346.5 1588.58   355.6 1591.98
#Mann= 3 , 0 , 0
       0      .1       0   174.8    .045       0   194.8      .1       0
Bank Sta=174.8,194.8
XS Rating Curve= 0 ,0
Exp/Cntr=0.3,0.1

Type RM Length L Ch R = 1 ,7364.4  ,195.7,177.5,161.2
XS GIS Cut Line= 4
     1893052.356      385373.049     1893080.134      385447.702
     1893120.064      385532.771     1893232.912      385661.243
#Sta/Elev= 28
       0 1568.72     8.8 1565.64    44.2  1552.3    70.8 1542.77    79.6 1539.47
      89 1535.68    98.4  1532.5   104.2 1531.38   107.8 1530.68   117.2 1530.41
   124.2 1530.95   126.6 1531.13     136 1532.47   154.8 1534.97   164.2 1535.96
   173.6 1536.69   183.1 1537.17   192.6 1537.52   230.6 1538.66   240.1 1539.03
   249.6 1539.64   259.1 1541.23   268.6 1543.66   287.6 1549.04   297.1 1551.47
   306.6 1553.38   316.1 1555.06   344.6 1559.66
#Mann= 3 , 0 , 0
       0      .1       0   104.2    .045       0   124.2      .1       0
Bank Sta=104.2,124.2
XS Rating Curve= 0 ,0
Exp/Cntr=0.3,0.1

Type RM Length L Ch R = 1 ,7186.9  ,240.1,229.7,216.2
XS GIS Cut Line= 4
     1892795.412      385475.479      1892894.37      385564.021
     1893059.301      385626.521     1893191.245      385690.757
#Sta/Elev= 30
       0 1561.26      19 1557.65    37.9 1553.87    47.4 1552.23    56.9 1550.75
    75.9 1548.02    85.4 1546.43   113.8 1540.24   132.8 1536.27   142.6 1534.62
   152.4 1533.12   162.2 1531.86     172 1530.81   181.8 1529.96   191.6 1529.38
   211.2 1528.77   239.1 1528.44   250.4 1528.31   259.1 1528.59   260.2 1528.62
     270 1529.58   289.6 1531.73   338.5 1537.88   358.1 1540.47   377.6 1542.56
   387.4  1543.9   397.2 1545.97   416.8 1550.56   426.6  1552.6   455.9 1557.65
#Mann= 3 , 0 , 0
       0      .1       0   239.1    .045       0   259.1      .1       0
Bank Sta=239.1,259.1
XS Rating Curve= 0 ,0
Exp/Cntr=0.3,0.1

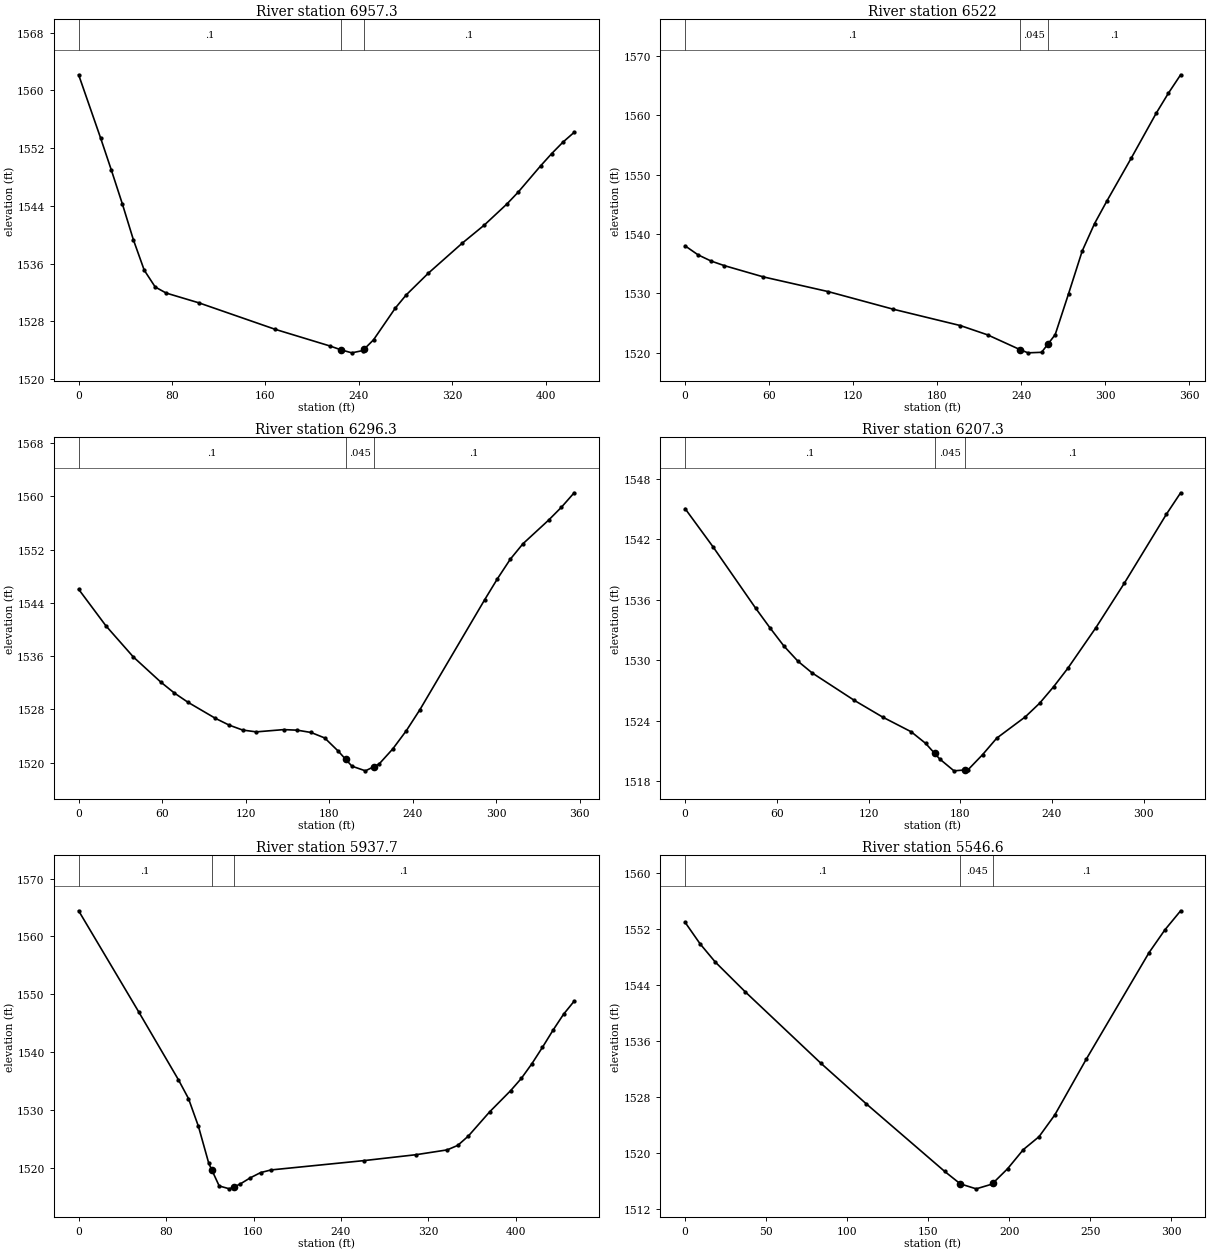
Type RM Length L Ch R = 1 ,6957.3  ,436.8,435.3,432.5
XS GIS Cut Line= 4
      1892738.12      385820.966     1892878.745      385819.229
     1893028.051      385817.493     1893156.523      385777.563
#Sta/Elev= 27
       0 1562.18    18.8 1553.42    28.1 1548.93    37.5 1544.25    46.9  1539.3
    56.2 1535.08    65.6 1532.75      75 1531.91   103.1 1530.55   168.6 1526.87
   215.3 1524.57   224.5 1524.05     234 1523.62   243.3 1523.93   244.5 1524.12
   252.6 1525.42   271.3 1529.83   280.6 1531.65   299.6 1534.67   328.4  1538.8
   347.6 1541.35   366.8 1544.25   376.4 1545.88   395.7 1549.54   405.3 1551.26
   414.9 1552.84   424.5  1554.2
#Mann= 3 , 0 , 0
       0      .1       0   224.5    .045       0   244.5      .1       0
Bank Sta=224.5,244.5
XS Rating Curve= 0 ,0
Exp/Cntr=0.3,0.1

Type RM Length L Ch R = 1 ,6522    ,211,225.7,240.1
XS GIS Cut Line= 4
     1893024.578      386072.702     1893182.564      386074.438
     1893307.564      386062.285     1893375.273      386043.188
#Sta/Elev= 22
       0    1538     9.3 1536.48    18.6 1535.44    27.9 1534.68    55.8 1532.78
   102.2  1530.3   148.7 1527.33   196.6 1524.58     216 1523.02   239.3 1520.52
   244.9 1519.99   254.6 1520.08   259.3 1521.52   264.3 1523.05   273.9 1529.97
   283.6 1537.13   292.4 1541.74   301.2 1545.54   318.8 1552.84   336.4 1560.31
   345.1 1563.68   353.9  1566.8
#Mann= 3 , 0 , 0
       0      .1       0   239.3    .045       0   259.3      .1       0
Bank Sta=239.3,259.3
XS Rating Curve= 0 ,0
Exp/Cntr=0.3,0.1

Type RM Length L Ch R = 1 ,6296.3  ,88.1,89,88.9
XS GIS Cut Line= 4
     1892975.967      386149.091     1893111.384      386228.952
     1893198.189      386274.091     1893293.676      386307.077
#Sta/Elev= 30
       0 1546.05    19.6 1540.56    39.3 1535.89      59 1532.12    68.8 1530.47
    78.6 1529.08    98.3 1526.67   108.1 1525.66   117.9 1524.91   127.7 1524.64
   147.4 1524.98   157.2 1524.89     167 1524.55   176.8 1523.73   186.6 1521.74
   191.9 1520.52   196.4 1519.49   206.1 1518.79   211.9 1519.39   215.9 1519.81
   225.7 1522.07   235.5 1524.82   245.3 1527.99   291.8 1544.48     301 1547.64
   310.2 1550.56   319.3 1552.88   337.7 1556.42   346.9 1558.35   356.1 1560.53
#Mann= 3 , 0 , 0
       0      .1       0   191.9    .045       0   211.9      .1       0
Bank Sta=191.9,211.9
XS Rating Curve= 0 ,0
Exp/Cntr=0.3,0.1

Type RM Length L Ch R = 1 ,6207.3  ,284.9,269.6,256.9
XS GIS Cut Line= 4
     1892930.828      386237.632     1893041.939      386282.771
     1893139.162      386338.327     1893225.967      386369.577
#Sta/Elev= 26
       0 1545.02    18.4 1541.21    46.1 1535.17    55.4 1533.24    64.6 1531.42
    73.8 1529.91      83 1528.76   110.7 1526.03   129.3 1524.37   147.9 1522.92
   157.3 1521.78   163.2 1520.79   166.6 1520.22   175.9 1519.05   183.2 1519.14
   185.2 1519.17   194.6 1520.65   203.9 1522.29   222.6  1524.4   231.9 1525.74
   241.1 1527.38   250.4 1529.21   268.8 1533.24   287.3 1537.62   314.9 1544.47
   324.2 1546.59
#Mann= 3 , 0 , 0
       0      .1       0   163.2    .045       0   183.2      .1       0
Bank Sta=163.2,183.2
XS Rating Curve= 0 ,0
Exp/Cntr=0.3,0.1

Type RM Length L Ch R = 1 ,5937.7  ,404,391.1,375.3
XS GIS Cut Line= 4
     1892816.245      386537.979      1892925.62      386531.035
     1893151.314      386501.521     1893264.162      386473.743
#Sta/Elev= 27
       0 1564.45    54.8 1547.01    91.3 1535.21   100.5 1531.96   109.6 1527.15
   119.1 1520.73   121.7 1519.66   128.6 1516.83     138 1516.33   141.7 1516.64
   147.5 1517.13     157 1518.23   166.5 1519.14     176  1519.6   261.3 1521.22
   308.8 1522.24   337.2 1523.07   346.9 1523.85   356.6 1525.47     376 1529.64
   395.3 1533.33     405 1535.43   414.7 1537.98   424.4 1540.83   434.1  1543.8
   443.7 1546.55   453.4 1548.81
#Mann= 3 , 0 , 0
       0      .1       0   121.7    .045       0   141.7      .1       0
Bank Sta=121.7,141.7
XS Rating Curve= 0 ,0
Exp/Cntr=0.3,0.1

Type RM Length L Ch R = 1 ,5546.6  ,238,242.3,246
XS GIS Cut Line= 3
     1893146.106      386791.452     1893239.856      386730.688
     1893397.842      386617.841
#Sta/Elev= 19
       0 1553.02     9.3 1549.93    18.6 1547.35    37.2 1543.07    83.8 1532.88
   111.7  1527.1   160.3  1517.4   169.9 1515.63   179.7 1514.92   189.4 1515.59
   189.9  1515.7   199.1  1517.8   208.8 1520.53   218.5 1522.38   228.2 1525.48
   247.6 1533.44   286.4 1548.69   296.2 1551.95   305.9 1554.67
#Mann= 3 , 0 , 0
       0      .1       0   169.9    .045       0   189.9      .1       0
Bank Sta=169.9,189.9
XS Rating Curve= 0 ,0
Exp/Cntr=0.3,0.1

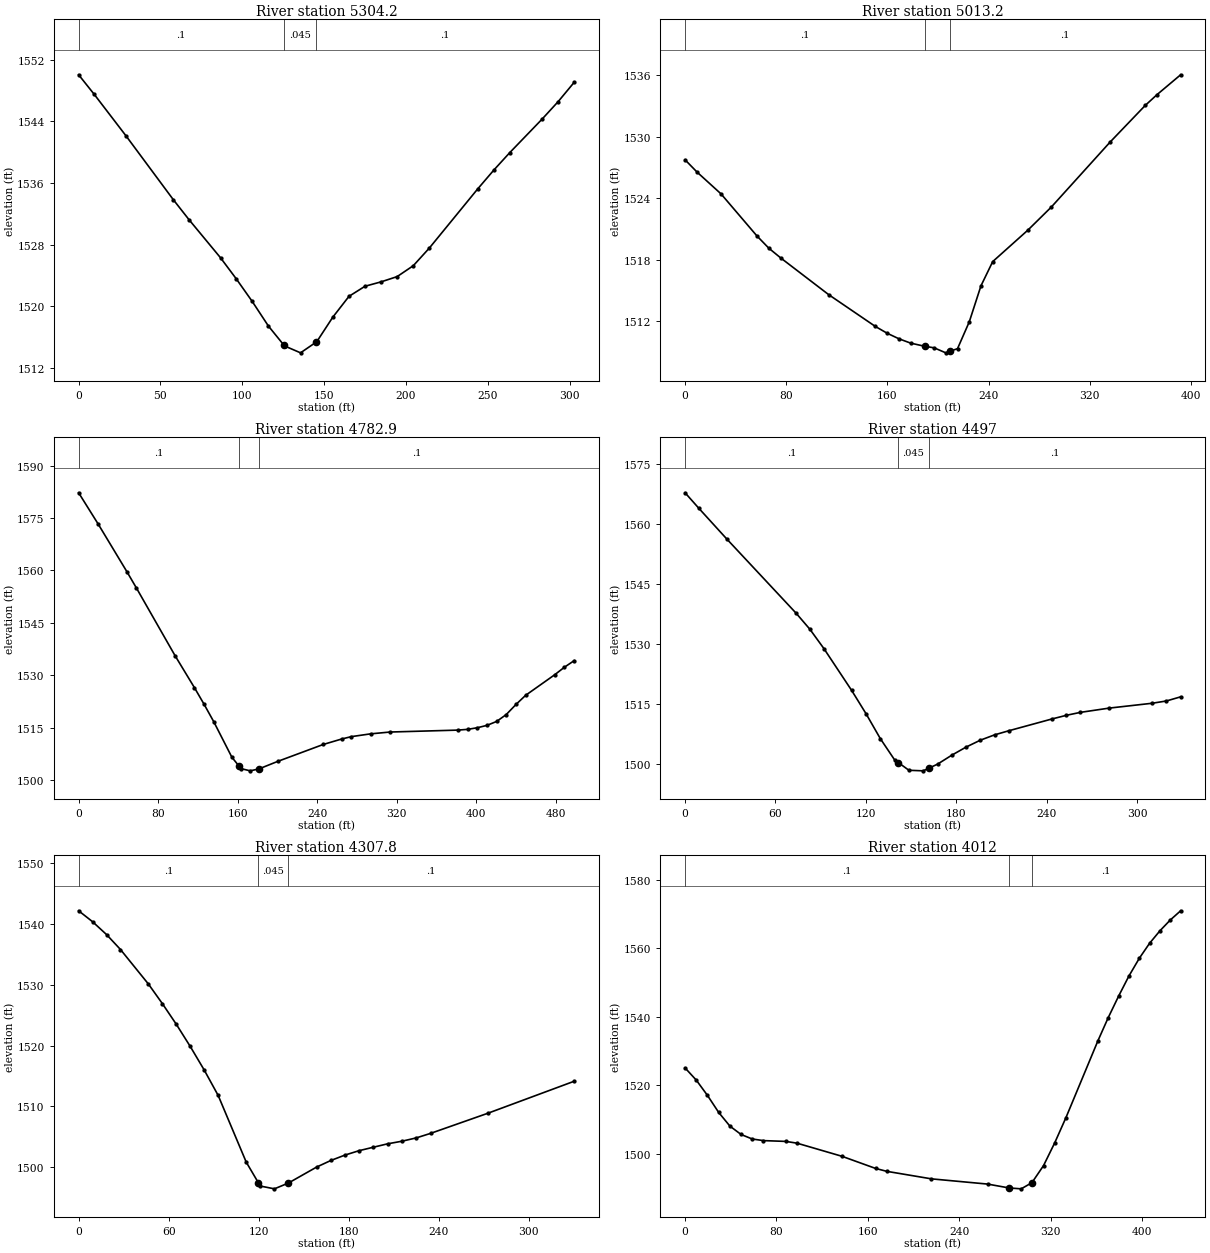
Type RM Length L Ch R = 1 ,5304.2  ,265.3,291,315.2
XS GIS Cut Line= 3
     1893248.537      386980.688     1893333.606      386935.549
     1893517.634      386841.799
#Sta/Elev= 27
       0 1550.06     9.6  1547.5    28.9 1542.14    57.8 1533.85    67.4 1531.25
    86.7 1526.29    96.3 1523.56   106.1 1520.61     116 1517.41   125.2    1515
   125.8 1514.84   135.6 1513.94   145.2 1515.34   145.5 1515.38   155.3 1518.57
   165.2 1521.28     175 1522.59   184.8 1523.16   194.6 1523.84   204.5 1525.26
   214.3 1527.55   243.8 1535.22   253.7 1537.68   263.5 1539.96   283.2  1544.3
     293 1546.57   302.8 1549.08
#Mann= 3 , 0 , 0
       0      .1       0   125.2    .045       0   145.2      .1       0
Bank Sta=125.2,145.2
XS Rating Curve= 0 ,0
Exp/Cntr=0.3,0.1

Type RM Length L Ch R = 1 ,5013.2  ,233.5,230.3,227.6
XS GIS Cut Line= 4
     1893304.092      387083.118     1893403.051      387138.674
     1893517.634      387199.438     1893665.203      387182.077
#Sta/Elev= 25
       0 1527.74     9.5 1526.54    28.4 1524.42    56.7 1520.33    66.2 1519.12
    75.7 1518.16   113.5 1514.59   150.5 1511.48   159.8 1510.82   169.1 1510.28
   178.3 1509.86   189.4 1509.55   196.9  1509.4   206.1 1508.91   209.4 1509.06
   215.4 1509.32   224.7 1511.94   233.9 1515.44   243.2 1517.81     271 1520.88
   289.6 1523.14     336 1529.47   363.9 1533.06   373.2 1534.11   391.8 1536.04
#Mann= 3 , 0 , 0
       0      .1       0   189.4    .045       0   209.4      .1       0
Bank Sta=189.4,209.4
XS Rating Curve= 0 ,0
Exp/Cntr=0.3,0.1

Type RM Length L Ch R = 1 ,4782.9  ,305.8,285.9,266
XS GIS Cut Line= 4
      1893144.37      387190.757     1893265.898      387251.521
     1893385.689      387298.396     1893588.814      387414.716
#Sta/Elev= 30
       0  1582.2    19.4 1573.38    48.5 1559.66    58.2 1554.94      97 1535.62
   116.5 1526.47   126.2 1521.72   135.9 1516.75   154.2 1506.56   161.4 1504.02
   163.4 1503.31   172.6 1502.67   181.4 1503.22   200.2 1505.36   246.1 1510.21
   264.5 1511.76   274.3 1512.45   293.8 1513.25   313.3 1513.77   381.5 1514.32
   391.3 1514.53     401 1514.99   410.8 1515.67   420.6  1516.8   430.3 1518.78
   440.1 1521.67   449.8 1524.28   479.1 1530.17   488.8 1532.31   498.6 1534.19
#Mann= 3 , 0 , 0
       0      .1       0   161.4    .045       0   181.4      .1       0
Bank Sta=161.4,181.4
XS Rating Curve= 0 ,0
Exp/Cntr=0.3,0.1

Type RM Length L Ch R = 1 ,4497    ,201.5,189.2,176.5
XS GIS Cut Line= 3
     1893213.814      387588.327     1893316.245       387546.66
     1893515.898      387458.118
#Sta/Elev= 27
       0 1567.85     9.2 1563.94    27.6 1556.33    73.7 1537.75    82.9 1533.71
    92.2 1528.88   110.6 1518.43   120.1 1512.64   129.6  1506.4   139.1 1501.08
   141.6  1500.4   148.6 1498.48   158.1 1498.34   161.6 1498.96   167.6 1500.01
     177 1502.24   186.6 1504.29     196    1506   205.5 1507.34     215 1508.37
   243.5  1511.3     253 1512.21   262.5 1512.96   281.5 1514.02     310 1515.23
   319.5  1515.8     329 1516.84
#Mann= 3 , 0 , 0
       0      .1       0   141.6    .045       0   161.6      .1       0
Bank Sta=141.6,161.6
XS Rating Curve= 0 ,0
Exp/Cntr=0.3,0.1

Type RM Length L Ch R = 1 ,4307.8  ,267.7,295.8,323.2
XS GIS Cut Line= 4
     1893359.648      387774.091     1893437.773      387708.118
     1893495.064      387633.466     1893564.509      387518.882
#Sta/Elev= 26
       0 1542.18     9.3 1540.38    18.6 1538.27    27.9 1535.81    46.5 1530.14
    55.8 1526.92    65.1 1523.52    74.4 1519.87    83.7    1516      93 1511.82
   111.7 1500.86   119.8 1497.46   121.1 1496.92   130.5 1496.46   139.8 1497.41
   158.7 1500.05   168.1 1501.12   177.5 1502.01     187 1502.74   196.4  1503.3
   205.9 1503.86   215.5 1504.29   225.1 1504.84   234.6 1505.58   272.9  1508.9
   330.3 1514.15
#Mann= 3 , 0 , 0
       0      .1       0   119.8    .045       0   139.8      .1       0
Bank Sta=119.8,139.8
XS Rating Curve= 0 ,0
Exp/Cntr=0.3,0.1

Type RM Length L Ch R = 1 ,4012    ,232.7,246.9,261.5
XS GIS Cut Line= 4
     1893415.203      387798.396     1893571.453      387784.507
     1893755.481      387814.021     1893845.759      387820.966
#Sta/Elev= 30
       0 1525.11     9.8 1521.56    19.6 1517.09    29.4 1512.14    39.2 1508.15
      49  1505.7    58.8 1504.38    68.6 1503.91    88.2 1503.68      98 1503.16
   137.3 1499.34   166.7  1495.8   176.5 1494.95   215.7 1492.75   264.8 1491.23
   283.6  1490.1   294.2 1489.84   303.6 1491.63   313.8 1496.63   323.6 1503.28
   333.4 1510.62   361.4 1533.05   370.4 1539.78   379.5 1546.07   388.5 1551.92
   397.6  1557.1   406.6 1561.48   415.7 1565.14   424.7 1568.27   433.8 1570.97
#Mann= 3 , 0 , 0
       0      .1       0   283.6    .045       0   303.6      .1       0
Bank Sta=283.6,303.6
XS Rating Curve= 0 ,0
Exp/Cntr=0.3,0.1

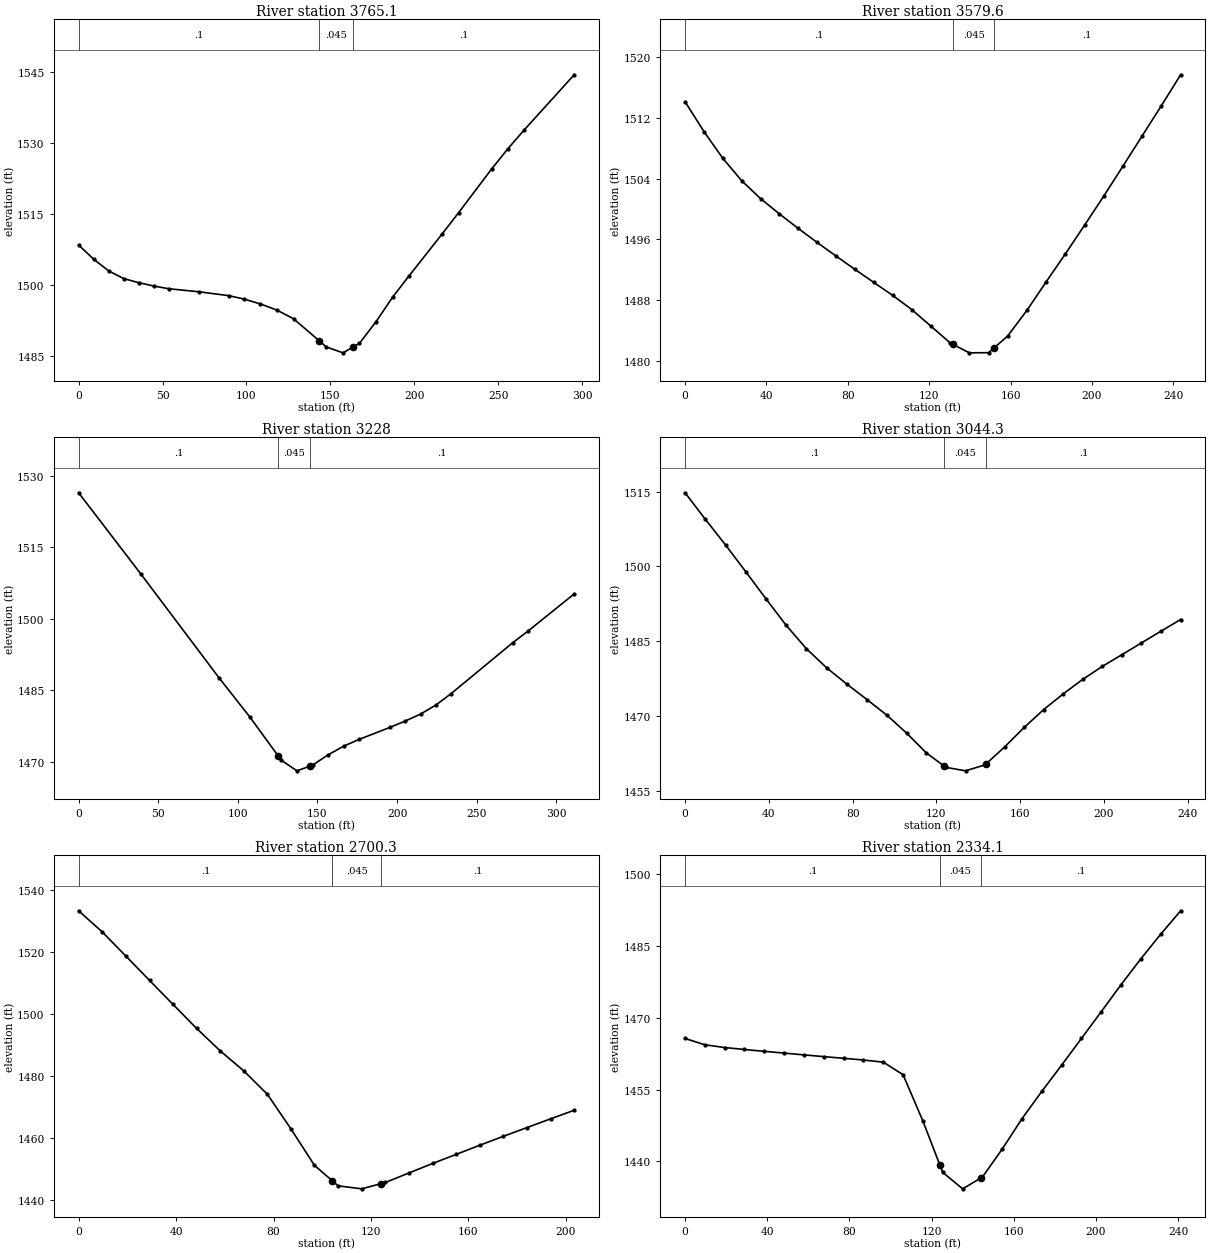
Type RM Length L Ch R = 1 ,3765.1  ,182.3,185.5,188.7
XS GIS Cut Line= 3
     1893418.676      387874.785     1893493.328      387939.021
     1893639.162      388070.966
#Sta/Elev= 27
       0  1508.5       9  1505.5    17.9 1503.05    26.9 1501.41    35.8 1500.56
    44.8 1499.85    53.7 1499.28    71.6 1498.64    89.5 1497.82    98.5  1497.1
   108.3 1496.07   118.2 1494.76     128 1492.94   143.4 1488.27   147.6 1486.98
   157.5 1485.75   163.4 1486.95   167.3 1487.75   177.2 1492.35     187 1497.48
   196.8 1501.98   216.5 1510.82   226.3 1515.31     246 1524.54   255.8 1528.87
   265.6 1532.86   295.2 1544.44
#Mann= 3 , 0 , 0
       0      .1       0   143.4    .045       0   163.4      .1       0
Bank Sta=143.4,163.4
XS Rating Curve= 0 ,0
Exp/Cntr=0.3,0.1

Type RM Length L Ch R = 1 ,3579.6  ,359.8,351.6,342.9
XS GIS Cut Line= 3
     1893283.259       387984.16     1893357.912      388053.604
     1893449.926      388161.243
#Sta/Elev= 29
       0 1514.13     9.3 1510.19    18.5  1506.7    27.8 1503.74    37.1 1501.38
    46.3 1499.38    55.6 1497.46    64.9 1495.61    74.2 1493.82    83.4 1492.08
    92.7 1490.36     102 1488.65   111.4 1486.78   120.8  1484.6   130.3 1482.39
   131.8 1482.18   139.7 1481.08   149.2  1481.1   151.8 1481.71   158.6  1483.3
     168 1486.66   177.5 1490.43   186.9 1494.09   196.4 1497.89   205.8 1501.71
   215.2 1505.64   224.7 1509.64   234.1  1513.6   243.6 1517.68
#Mann= 3 , 0 , 0
       0      .1       0   131.8    .045       0   151.8      .1       0
Bank Sta=131.8,151.8
XS Rating Curve= 0 ,0
Exp/Cntr=0.3,0.1

Type RM Length L Ch R = 1 ,3228    ,178.3,183.7,189.5
XS GIS Cut Line= 3
     1892982.912      388206.382     1893127.009      388289.716
     1893260.689      388345.271
#Sta/Elev= 20
       0 1526.41    39.2 1509.34    88.1 1487.67   107.7 1479.35   125.2 1471.33
   127.3 1470.37   137.1 1468.15   145.2 1469.13   146.9 1469.34   156.7 1471.51
   166.5 1473.33   176.1 1474.73   195.4 1477.24   205.1 1478.58   214.7 1480.04
   224.4 1481.94     234 1484.35   272.6 1494.99   282.3 1497.46   311.2 1505.22
#Mann= 3 , 0 , 0
       0      .1       0   125.2    .045       0   145.2      .1       0
Bank Sta=125.2,145.2
XS Rating Curve= 0 ,0
Exp/Cntr=0.3,0.1

Type RM Length L Ch R = 1 ,3044.3  ,356.6,343.9,330.6
XS GIS Cut Line= 3
     1892883.953      388333.118     1892960.342      388392.146
     1893062.773      388487.632
#Sta/Elev= 28
       0 1514.76     9.6 1509.48    19.3  1504.3      29 1498.92    38.6 1493.51
    48.3 1488.16    57.9 1483.51    67.6 1479.66    77.2 1476.41    86.9 1473.28
    96.5 1470.11   105.9 1466.52   115.2  1462.6   123.7 1459.96   124.5 1459.71
   133.9 1459.01   143.2 1460.21   143.7  1460.4   152.6 1463.82   161.9 1467.71
   171.2 1471.29   180.6 1474.46   189.9 1477.36   199.2 1479.95   208.6 1482.31
   217.9 1484.66   227.2 1487.01   236.6 1489.35
#Mann= 3 , 0 , 0
       0      .1       0   123.7    .045       0   143.7      .1       0
Bank Sta=123.7,143.7
XS Rating Curve= 0 ,0
Exp/Cntr=0.3,0.1

Type RM Length L Ch R = 1 ,2700.3  ,367.8,366.2,364.5
XS GIS Cut Line= 2
     1892640.898      388619.577     1892838.814      388666.452
#Sta/Elev= 24
       0 1533.22     9.7 1526.39    19.4 1518.58    29.1 1510.75    38.7 1503.03
    48.4 1495.26    58.1    1488    67.8 1481.53    77.5 1473.95    87.2 1462.74
    96.8 1451.03   104.1 1446.06   106.5 1444.42   116.2 1443.45   124.1 1445.12
   125.9  1445.5   135.6 1448.58   145.3 1451.64     155 1454.59   164.6 1457.51
   174.3  1460.4     184 1463.22   193.7 1466.04   203.4 1468.82
#Mann= 3 , 0 , 0
       0      .1       0   104.1    .045       0   124.1      .1       0
Bank Sta=104.1,124.1
XS Rating Curve= 0 ,0
Exp/Cntr=0.3,0.1

Type RM Length L Ch R = 1 ,2334.1  ,270.1,281.6,292.8
XS GIS Cut Line= 2
     1892594.023      388987.632      1892831.87      389027.563
#Sta/Elev= 28
       0 1465.67     9.6 1464.36    19.3 1463.78    28.9 1463.37    38.6 1462.98
    48.2 1462.62    57.9 1462.24    67.5 1461.88    77.2 1461.53    86.8 1461.17
    96.5 1460.72   106.1  1458.1   115.8 1448.36     124 1439.24   125.4 1437.68
   135.1 1434.24     144 1436.51   144.7 1436.69   154.4 1442.58     164 1448.91
   173.6  1454.6   183.3 1460.11   192.9 1465.67   202.6  1471.3   212.2 1476.92
   221.9 1482.36   231.5 1487.47   241.2 1492.37
#Mann= 3 , 0 , 0
       0      .1       0     124    .045       0     144      .1       0
Bank Sta=124,144
XS Rating Curve= 0 ,0
Exp/Cntr=0.3,0.1

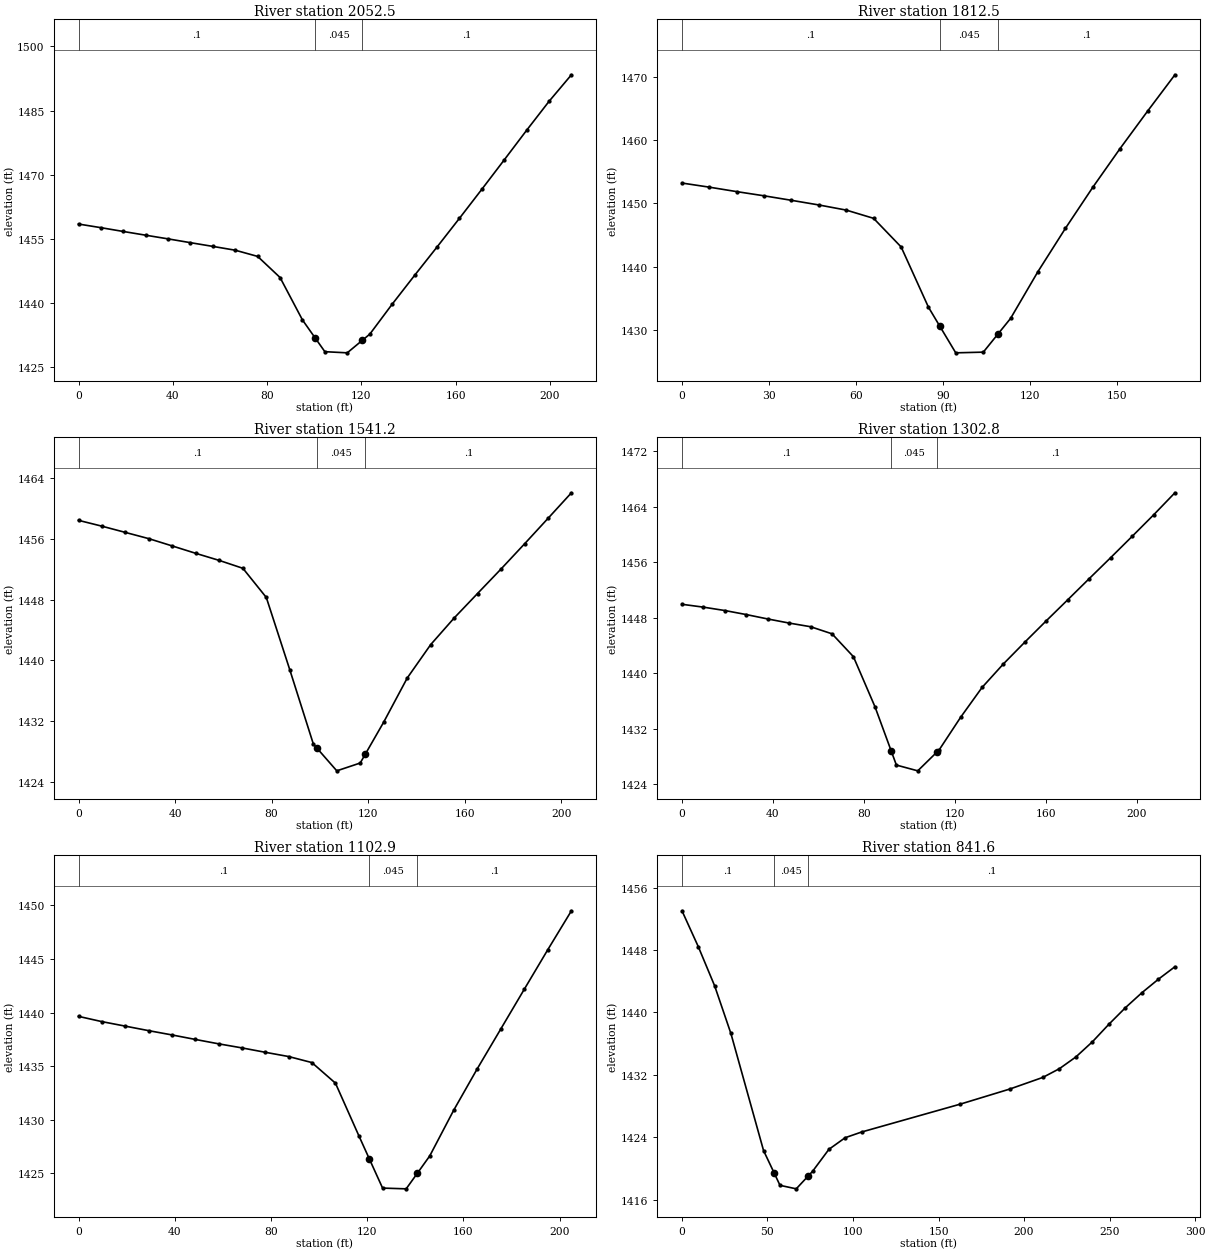
Type RM Length L Ch R = 1 ,2052.5  ,232.3,240,247.5
XS GIS Cut Line= 2
     1892514.162      389197.702     1892684.301      389319.229
#Sta/Elev= 25
       0 1458.48     9.5 1457.63      19 1456.74    28.5 1455.87      38 1455.01
    47.5 1454.12      57 1453.25    66.5 1452.36      76 1450.91    85.5 1445.98
      95 1436.06   100.4 1431.84   104.5 1428.64     114 1428.37   120.4  1431.3
   123.6 1432.76     133  1439.7   142.6  1446.5   152.1 1453.12   161.6 1459.82
   171.1 1466.61   180.6 1473.48   190.1  1480.4   199.6 1487.16   209.1 1493.37
#Mann= 3 , 0 , 0
       0      .1       0   100.4    .045       0   120.4      .1       0
Bank Sta=100.4,120.4
XS Rating Curve= 0 ,0
Exp/Cntr=0.3,0.1

Type RM Length L Ch R = 1 ,1812.5  ,267.5,271.3,275
XS GIS Cut Line= 2
     1892368.328      389345.271     1892470.759      389480.688
#Sta/Elev= 21
       0  1453.2     9.4 1452.55    18.9 1451.84    28.3 1451.18    37.7 1450.47
    47.2 1449.73    56.6 1448.92      66 1447.62    75.5 1443.09    84.9 1433.57
    88.8 1430.57    94.3 1426.35   103.8 1426.46   108.8  1429.3   113.2  1431.8
   122.6 1439.18   132.1 1446.05   141.5 1452.52   150.9 1458.65   160.4 1464.58
   169.8 1470.32
#Mann= 3 , 0 , 0
       0      .1       0    88.8    .045       0   108.8      .1       0
Bank Sta=88.8,108.8
XS Rating Curve= 0 ,0
Exp/Cntr=0.3,0.1

Type RM Length L Ch R = 1 ,1541.2  ,238.7,238.4,237.4
XS GIS Cut Line= 2
     1892133.953      389402.563     1892229.439      389583.118
#Sta/Elev= 24
       0 1458.46     9.7 1457.69    19.4 1456.87    29.2 1456.04    38.9 1455.08
    48.6 1454.11    58.4 1453.17    68.1 1452.14    77.8  1448.3    87.5  1438.8
    97.3 1428.98    98.8 1428.44     107 1425.46   116.7 1426.49   118.8 1427.65
   126.4 1431.86   136.2  1437.7   145.9 1442.09   155.6 1445.59   165.3 1448.82
   175.1 1452.07   184.8 1455.37   194.5 1458.72   204.2 1462.09
#Mann= 3 , 0 , 0
       0      .1       0    98.8    .045       0   118.8      .1       0
Bank Sta=98.8,118.8
XS Rating Curve= 0 ,0
Exp/Cntr=0.3,0.1

Type RM Length L Ch R = 1 ,1302.8  ,193.9,200,206.2
XS GIS Cut Line= 2
      1891925.62      389522.354     1892031.523      389711.591
#Sta/Elev= 26
       0 1449.93     9.4 1449.52    18.9 1449.03    28.3 1448.45    37.7 1447.82
    47.1 1447.23    56.6  1446.7      66 1445.68    75.4 1442.39    84.9 1435.17
      92 1428.84    94.3 1426.79   103.7 1425.96     112 1428.62   113.1 1428.97
   122.6 1433.69     132 1437.97   141.4 1441.36   150.9 1444.52   160.3 1447.58
   169.7 1450.59   179.1 1453.62   188.6 1456.66     198 1459.71   207.4 1462.79
   216.8 1465.98
#Mann= 3 , 0 , 0
       0      .1       0      92    .045       0     112      .1       0
Bank Sta=92,112
XS Rating Curve= 0 ,0
Exp/Cntr=0.3,0.1

Type RM Length L Ch R = 1 ,1102.9  ,247.8,261.3,273.7
XS GIS Cut Line= 3
     1891807.564      389572.702     1891790.203      389668.188
     1891817.981      389772.354
#Sta/Elev= 24
       0 1439.65     9.7 1439.16    19.4 1438.74    29.1 1438.32    38.8 1437.92
    48.5  1437.5    58.2 1437.09    67.9 1436.71    77.6  1436.3    87.4  1435.9
      97 1435.34   106.8 1433.42   116.6 1428.48   120.9 1426.35   126.4 1423.63
   136.2 1423.56   140.9 1425.03     146 1426.63   155.9 1430.87   165.7 1434.74
   175.5 1438.46   185.3 1442.18   195.1 1445.88   204.9  1449.5
#Mann= 3 , 0 , 0
       0      .1       0   120.9    .045       0   140.9      .1       0
Bank Sta=120.9,140.9
XS Rating Curve= 0 ,0
Exp/Cntr=0.3,0.1

Type RM Length L Ch R = 1 ,841.6   ,210.8,190.5,170.2
XS GIS Cut Line= 3
     1891599.231      389524.091     1891571.453      389635.202
     1891566.245      389808.813
#Sta/Elev= 24
       0 1453.02     9.5 1448.44    19.1  1443.4    28.6  1437.3    47.7 1422.29
    53.9 1419.42    57.3 1417.84    66.8 1417.39    73.9 1419.06    76.4 1419.65
    85.9 1422.45    95.4 1423.94     105 1424.67   162.8 1428.25   191.7 1430.18
     211 1431.67   220.7 1432.79   230.3 1434.29     240 1436.24   249.6 1438.48
   259.3 1440.61   268.9 1442.52   278.6 1444.26   288.2 1445.85
#Mann= 3 , 0 , 0
       0      .1       0    53.9    .045       0    73.9      .1       0
Bank Sta=53.9,73.9
XS Rating Curve= 0 ,0
Exp/Cntr=0.3,0.1