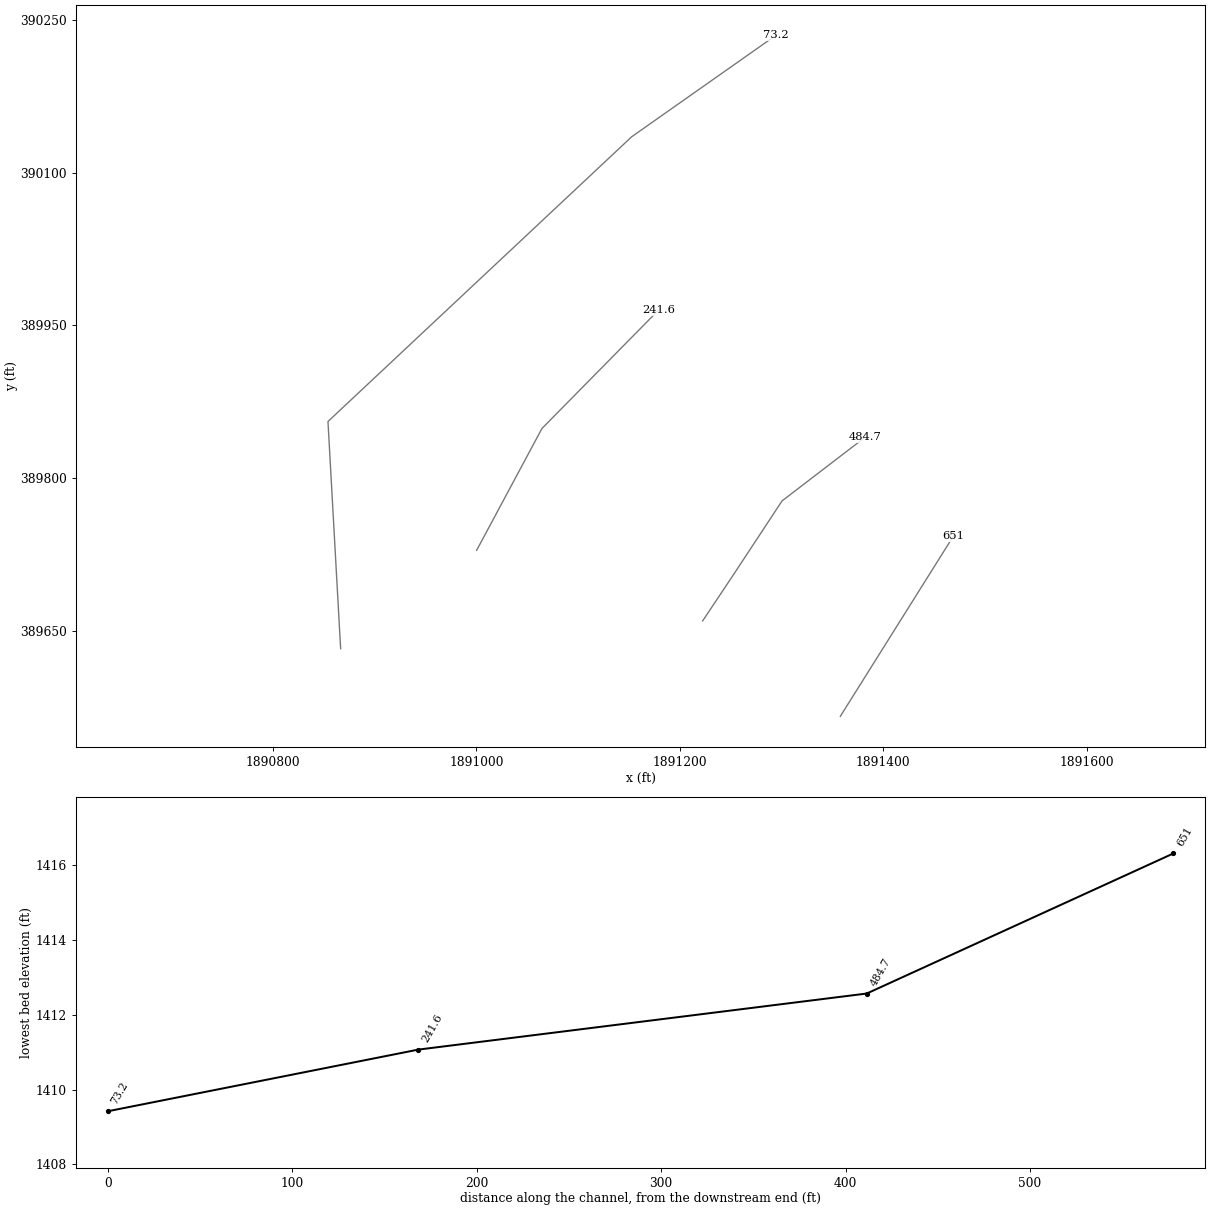
HEC-RAS study BULLRN1.prj: BULLRN1

--- BULLRN1.g01 (geometry) --- (continued)

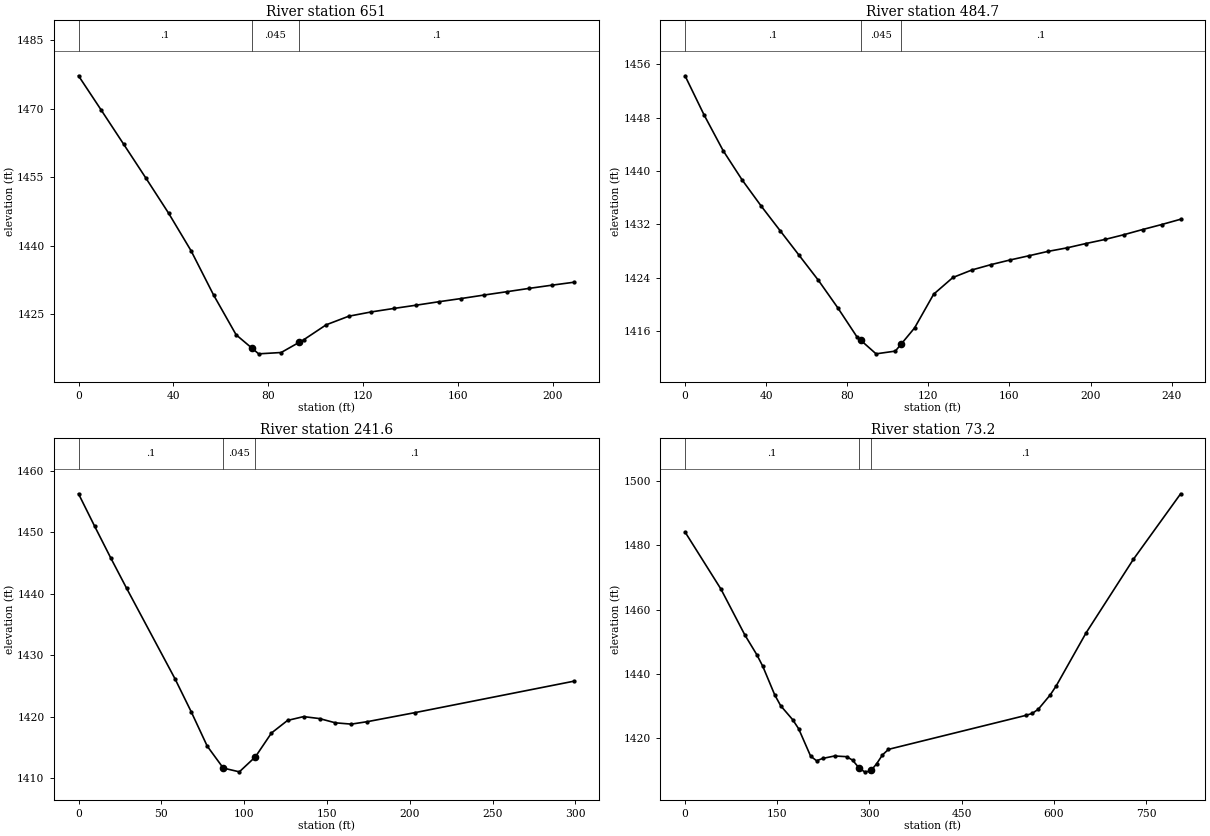
Type RM Length L Ch R = 1 ,651     ,166.7,166.3,166
XS GIS Cut Line= 2
     1891357.912      389565.757     1891469.023      389742.841
#Sta/Elev= 25
       0 1477.23     9.5 1469.78      19 1462.28    28.5 1454.76      38 1447.14
    47.5 1438.89      57  1429.2    66.5 1420.49      73 1417.64      76 1416.32
    85.5 1416.61      93 1418.81      95  1419.4   104.5 1422.68     114 1424.56
   123.5  1425.5     133 1426.26   142.5 1426.98     152 1427.73   161.5 1428.44
     171 1429.19   180.6 1429.92     190 1430.65   199.6 1431.35   209.1 1432.01
#Mann= 3 , 0 , 0
       0      .1       0      73    .045       0      93      .1       0
Bank Sta=73,93
XS Rating Curve= 0 ,0
Exp/Cntr=0.3,0.1

Type RM Length L Ch R = 1 ,484.7   ,240.7,243.1,245.2
XS GIS Cut Line= 4
     1891222.495      389659.507     1891253.745      389706.382
      1891300.62      389777.563     1891382.217      389840.063
#Sta/Elev= 29
       0  1454.3     9.4 1448.42    18.8 1443.06    28.2 1438.65    37.6 1434.73
      47 1431.01    56.3 1427.34    65.8 1423.59    75.3 1419.49    84.8 1415.11
    86.6 1414.62    94.2 1412.57   103.7 1412.98   106.6 1414.04   113.2 1416.46
   122.6 1421.52   132.1 1424.03   141.6 1425.17   150.9 1425.96   160.2 1426.65
   169.6 1427.29   178.9 1427.94   188.3 1428.47   197.6 1429.12     207 1429.73
   216.3 1430.44   225.7 1431.23     235 1431.97   244.4 1432.77
#Mann= 3 , 0 , 0
       0      .1       0    86.6    .045       0   106.6      .1       0
Bank Sta=86.6,106.6
XS Rating Curve= 0 ,0
Exp/Cntr=0.3,0.1

Type RM Length L Ch R = 1 ,241.6   ,176.5,168.4,160
XS GIS Cut Line= 3
     1891000.273      389728.952     1891064.509      389848.743
     1891179.092      389965.063
#Sta/Elev= 19
       0 1456.23     9.7 1450.98    19.4 1445.84    29.1 1440.85    58.2 1426.21
      68 1420.85    77.7 1415.25    87.4 1411.68    97.1 1411.07   106.8 1413.51
   116.5 1417.38   126.2 1419.42   135.9 1420.04   145.5 1419.72   155.1 1419.03
   164.7 1418.82   174.4 1419.22   203.2 1420.69   299.2  1425.8
#Mann= 3 , 0 , 0
       0      .1       0    87.4    .045       0   106.8      .1       0
#XS Ineff= 2 , 0
                           136.1         1419.99
Permanent Ineff=
       F       F
Bank Sta=87.4,106.8
XS Rating Curve= 0 ,0
Exp/Cntr=0.3,0.1

Type RM Length L Ch R = 1 ,73.2    ,73.4,73.2,73
BEGIN DESCRIPTION:
Known WSEL from Lettered XS 'I'
END DESCRIPTION:
XS GIS Cut Line= 4
     1890866.539      389632.195     1890854.093      389855.603
       1891152.8      390135.641     1891294.374       390235.21
#Sta/Elev= 30
       0 1484.17    58.4 1466.38    97.3 1452.08   116.7 1445.95   126.5 1442.31
   145.9 1433.41   155.6 1430.02   175.1 1425.68   184.8 1422.86   204.3 1414.32
     214 1412.87   223.8 1413.59   243.2 1414.36   262.8 1414.15   272.5 1413.07
   283.1 1410.65     292 1409.42   301.7 1409.64   303.1 1409.96   311.5 1411.88
   321.2 1414.69     331 1416.43   555.2 1427.05     565 1427.65   574.7 1428.93
   594.2 1433.41     604 1436.25   652.4 1452.71   729.4 1475.65   806.3 1496.08
#Mann= 3 , 0 , 0
       0      .1       0   283.1    .045       0   303.1      .1       0
Bank Sta=283.1,303.1
XS Rating Curve= 0 ,0
Exp/Cntr=0.3,0.1

Chan Stop Cuts=-1
Use User Specified Reach Order=0
Composite Channel Slope=5